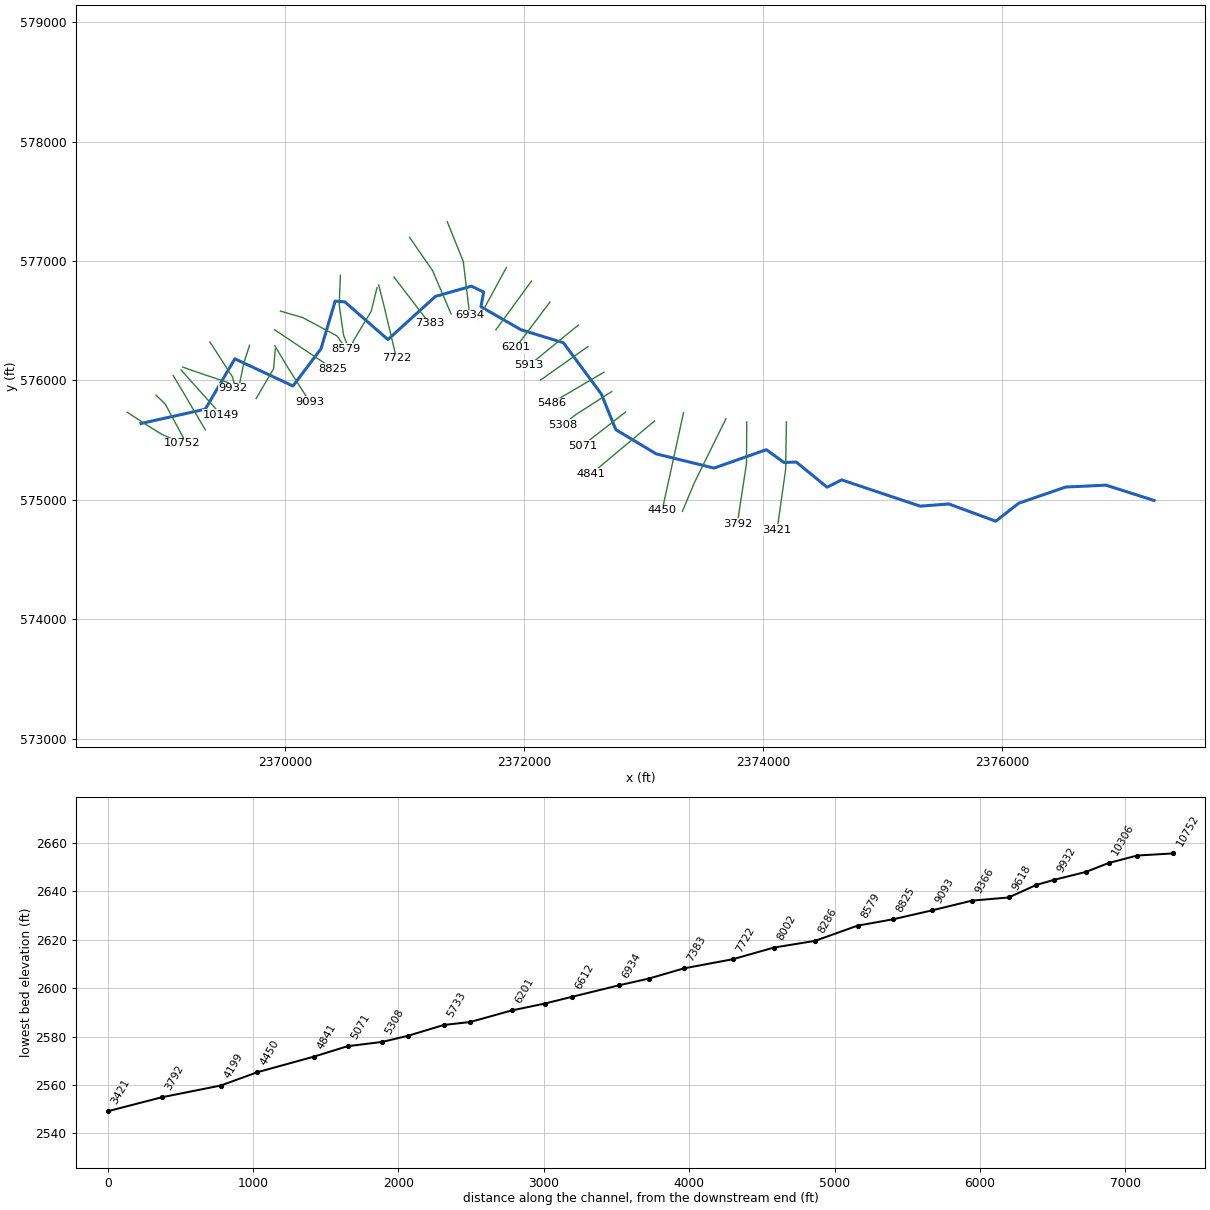
--- LAURELFK.prj (project) ---

Proj Title=LAURELFK
Current Plan=p01
Default Exp/Contr=0,0
English Units
Geom File=g01
Flow File=f01
Plan File=p01
BEGIN DESCRIPTION:
Stream Name: Laurel Fork
Flod Zone: Zone A
Pendleton County, WV
WVDHSEM Flood Warning & Analysis Mapping
HEC-RAS Version 5.0.7
Hydrology Method: Regression
Model Notes:
Known Water Surface Elevation from North Fork South Branch Potomac River
END DESCRIPTION:
DSS Export Rating Curves= 0
DSS Export Rating Curve Sorted= 0
DSS Export Volume Flow Curves= 0
DXF OffsetX= 0
DXF OffsetY= 0
DXF ScaleX= 0
DXF ScaleY= 0

--- LAURELFK.p01 (plan) ---

Plan Title=Floodplain
Program Version=4.00
Geom File=g01
Flow File=f01
K Sum by GR=0
Std Step Tol=0.01
Critical Tol=0.01
Num of Std Step Trials=20
Max Error Tol=0.3
Flow Tol Ratio=0.001
Split Flow NTrial=30
Split Flow Tol=0.02
Split Flow Ratio=0.02
Log Output Level=0
Friction Slope Method=1
Unsteady Friction Slope Method=2
Unsteady Bridges Friction Slope Method=1
Global Log Level=0
CheckData=False
Run HTab=0
Run UNet=0
Run PostProcess=0
UNET Theta=0
UNET Theta Warmup=0
UNET ZTol=0
UNET ZSATol=0
UNET MxIter=0
UNET MaxInSteps=0
UNET DtIC=0
UNET DtMin=0
UNET MaxCRTS=0
UNET WFStab=0
UNET SFStab=0
UNET WFX=0
UNET SFX=0
UNET DSS MLevel=0
UNET DZMax Abort=0
UNET Convert EG Bridges=0
UNET Use Existing IB Tables=0
UNET Froude Limit=0
UNET Froude Power=0
Write IC File=0
Echo Input=False
Echo Output=False
Write Detailed=0

--- LAURELFK.f01 (steady flow) ---

Flow Title=Flows
Program Version=5.07
Number of Profiles= 6
Profile Names=P100yr,P10yr,P25yr,P50yr,P500yr,P101yr
River Rch & RM=LAURELFK,Main            ,10752
    5291    2393    3435    4334    7938    6439
River Rch & RM=LAURELFK,Main            ,6934
    6290    2838    4078    5149    9454    7655
River Rch & RM=LAURELFK,Main            ,0
    9063    4066    5858    7410   13675   11030
Boundary for River Rch & Prof#=LAURELFK,Main            , 1
Up Type= 0
Dn Type= 1
Dn Known WS=2502.08
Boundary for River Rch & Prof#=LAURELFK,Main            , 2
Up Type= 0
Dn Type= 1
Dn Known WS=2500.92
Boundary for River Rch & Prof#=LAURELFK,Main            , 3
Up Type= 0
Dn Type= 1
Dn Known WS=2501.63
Boundary for River Rch & Prof#=LAURELFK,Main            , 4
Up Type= 0
Dn Type= 1
Dn Known WS=2501.71
Boundary for River Rch & Prof#=LAURELFK,Main            , 5
Up Type= 0
Dn Type= 1
Dn Known WS=2502.58
Boundary for River Rch & Prof#=LAURELFK,Main            , 6
Up Type= 0
Dn Type= 1
Dn Known WS=2502.23
DSS Import GetInterval= 0
DSS Import GetPeak= 0
DSS Import FillOption= 0

--- LAURELFK.g01 (geometry) ---

Geom Title=Geometry
Program Version=5.07

River Reach=LAURELFK        ,Main
Reach XY= 30
 2368793.2308276575638.5371049052369330.87837431575758.380697221
2369578.33260384576179.9097098262370064.68760225575952.568629071
2370299.16055849 576263.782901662370417.73676494576663.136105582
2370498.63916215576657.1485847232370859.57610431576341.317523494
2371257.34893084576702.7935065782371558.48973274576788.445566237
2371661.11780831 576739.085428732371638.29075423576616.485936388
2371972.79435036576423.6047604982372327.84810218576314.782143474
2372645.55809665575885.536610901 2372766.9351505575586.932877392
2373105.07456607575383.8351864812373588.75962231575264.945332393
2374026.22462666575418.8472555732374174.36114138575311.765448749
2374277.27235287575315.5357823972374535.20392364575104.756020233
2374656.83228931575166.1564879722375314.73090789574945.904631898
2375553.47157216574964.6021010732375946.76999813574820.064004332
2376138.48746246574970.2156068982376531.35445887575106.060479566
2376869.62838867575121.9603821492377271.78320187 574993.78603889

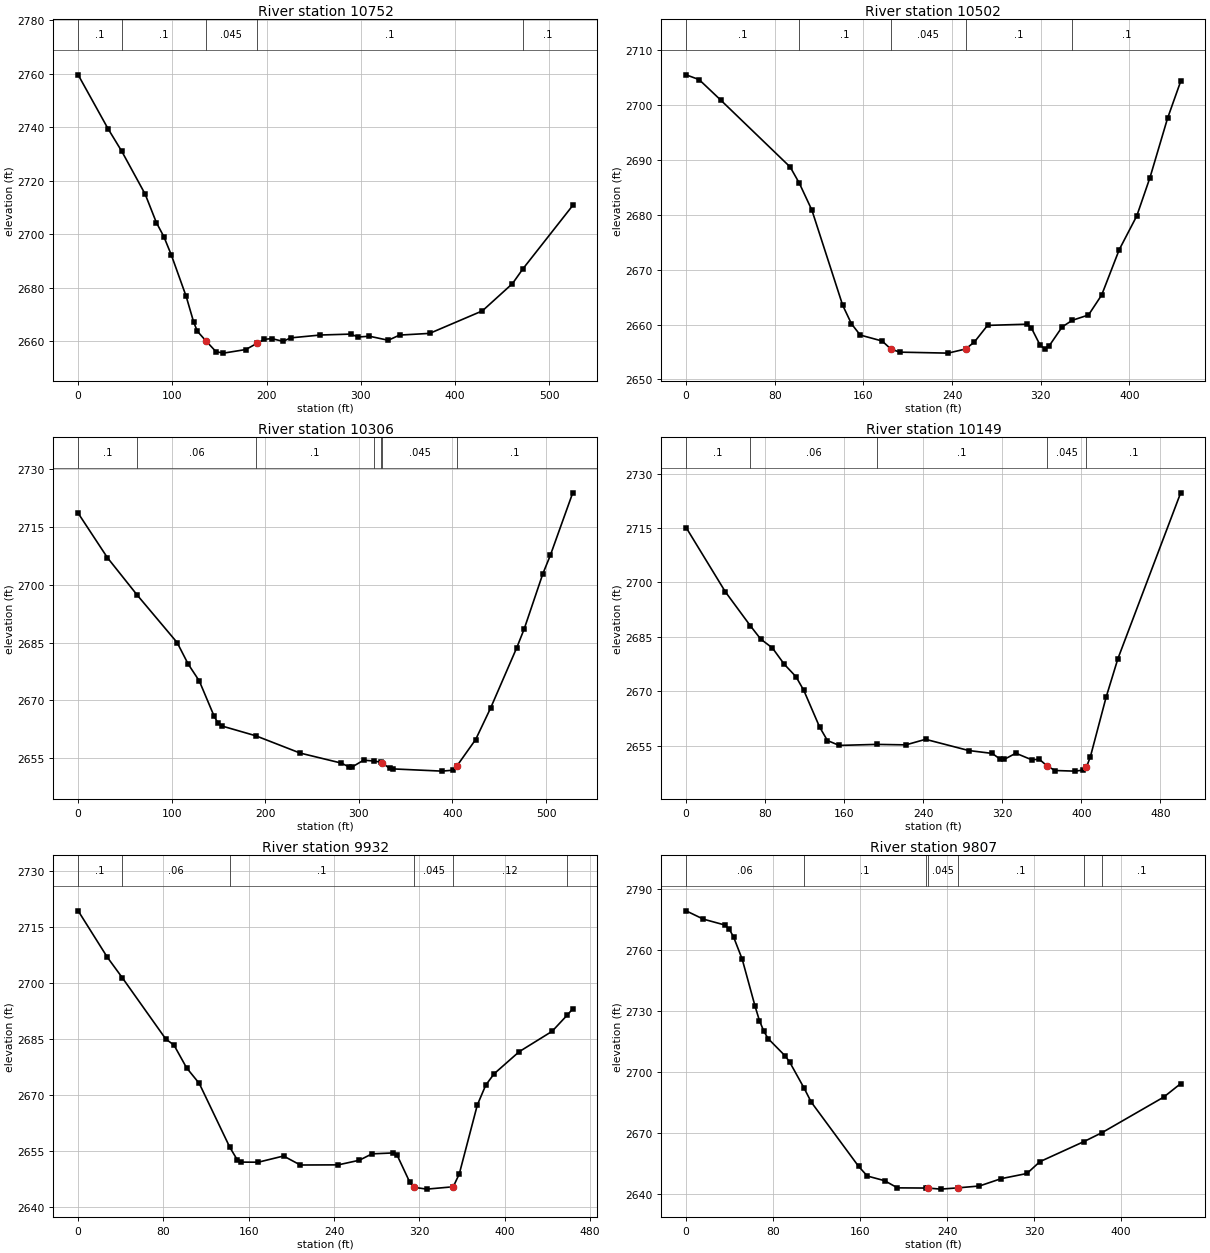
Type RM Length L Ch R = 1 ,10752   ,253.9,249.5,232.8
XS GIS Cut Line= 4
2368676.91117831575732.2869173882368882.92979513 575599.47451897
2368964.52707289575549.127506807 2369132.0618428575473.606332392
#Sta/Elev= 30
       0 2759.53   31.63 2739.46   46.27    2731   71.16 2714.96   83.02 2704.37
   90.93 2699.14   98.84 2692.32  114.65  2676.8  122.56 2667.24  126.51  2663.8
   135.5 2660.27  146.28  2656.2  154.19 2655.66  177.91    2657  189.77 2659.33
  197.68 2660.82  205.58 2661.08  217.44 2660.03  225.35 2661.35   257.1 2662.42
  289.06 2662.76  297.05 2661.67  309.04 2661.97  329.01 2660.46     341 2662.39
  372.96 2663.03  428.89 2671.43  460.85 2681.62  471.94 2687.14  524.77 2710.77
#Mann= 5 ,-1 , 0
       0      .1       0   46.27      .1       0   135.5    .045       0
  189.77      .1       0  471.94      .1       0
Bank Sta=135.5,189.77
XS Rating Curve= 0 ,0
Exp/Cntr=0.3,0.1

Type RM Length L Ch R = 1 ,10502   ,197.5,196.2,205.4
XS GIS Cut Line= 3
2368919.53274031575875.5162897262368997.65791214575798.693280637
2369156.51192513575501.818218231
#Sta/Elev= 30
       0 2705.56   11.74 2704.69   31.31 2700.94   93.92 2688.74  102.18 2685.78
  113.53 2680.86  141.26 2663.53  149.18 2660.14   157.1 2658.08  176.91 2656.99
  184.69 2655.54  192.75 2654.96  236.33 2654.78  252.17 2655.53   260.1  2656.8
  271.98 2659.84  307.63 2660.06  311.59 2659.36  319.51  2656.2  323.47 2655.61
  327.44 2656.05  339.32 2659.56  348.36 2660.76  363.09 2661.74  374.97 2665.38
  390.82 2673.66  406.66 2679.82  418.54  2686.8  434.39 2697.61  446.27 2704.38
#Mann= 5 ,-1 , 0
       0      .1       0  102.18      .1       0  184.69    .045       0
  252.17      .1       0  348.36      .1       0
Bank Sta=184.69,252.17
XS Rating Curve= 0 ,0
Exp/Cntr=0.3,0.1

Type RM Length L Ch R = 1 ,10306   ,156.6,157.6,162.3
XS GIS Cut Line= 3
2369062.61742789576039.5786256492369125.11730289575935.412167311
2369331.71465872575584.717658728
#Sta/Elev= 30
       0 2718.54   31.35 2706.98   63.31 2697.25   105.8    2685  117.56 2679.44
  129.46 2675.05  145.42 2665.86  149.41 2664.17   153.4  2663.4  189.79 2660.85
   237.2 2656.37   281.1 2653.78  289.08 2652.82  293.07 2652.81  305.04 2654.53
  315.89 2654.31   323.5 2654.01  324.96 2653.79  332.97  2652.4  336.96 2652.26
  388.84 2651.69  400.81 2651.94   404.8 2653.06  424.75 2659.88  440.71 2668.02
  468.65 2683.66  476.63 2688.54  496.58 2702.86  504.56 2707.61   528.5 2723.81
#Mann= 7 ,-1 , 0
       0      .1       0   63.31     .06       0  189.79      .1       0
  315.89      .1       0   323.5      .1       0  324.96    .045       0
   404.8      .1       0
Bank Sta=324.96,404.8
XS Rating Curve= 0 ,0
Exp/Cntr=0.3,0.1

Type RM Length L Ch R = 1 ,10149   ,209.2,216.8,229.5
XS GIS Cut Line= 2
 2369128.5894088576086.4535318912369461.92273164575713.189842731
#Sta/Elev= 30
       0 2715.16   39.72 2697.43   65.02 2688.06   75.46 2684.41   87.38 2681.93
   99.29 2677.47  111.21 2674.02  119.15 2670.22  135.04 2660.18  142.98 2656.43
   154.9 2655.08  192.86 2655.36  222.42 2655.23  242.27 2656.76  285.96 2653.67
  309.79 2652.87  317.74 2651.29  321.71  2651.2  333.62 2652.93  349.51 2651.14
  357.45 2651.24  365.43 2649.39  373.34 2648.16   393.2 2647.99  401.14 2648.24
  405.12 2649.13  409.09 2651.97  424.97 2668.35  436.89 2678.98  500.44 2724.72
#Mann= 5 ,-1 , 0
       0      .1       0   65.02     .06       0  192.86      .1       0
  365.43    .045       0  405.12      .1       0
Bank Sta=365.43,405.12
XS Rating Curve= 0 ,0
Exp/Cntr=0.3,0.1

Type RM Length L Ch R = 1 ,9932    ,136.4,125.1,119
XS GIS Cut Line= 4
2369142.47848864576110.7592575552369234.49241222576077.773103058
2369522.68671772 575980.550856562369560.88119514575931.939733312
#Sta/Elev= 30
       0 2719.31   27.37 2706.87   41.39 2701.39   82.11 2684.99   89.93 2683.31
   101.7 2677.24  113.55 2673.07  142.26 2655.93   149.1 2652.66  153.05    2652
  168.85 2651.97  192.55 2653.63  208.35 2651.22   243.9 2651.26  263.65  2652.5
   275.5 2654.21  295.25 2654.45   299.2 2653.77  311.05 2646.54     315 2645.24
  326.85 2644.76  351.67 2645.39  357.33 2648.82  374.25 2667.29  382.15 2672.62
  390.05 2675.67  413.49 2681.57   444.4 2687.04  458.75 2691.44  463.72 2693.06
#Mann= 6 ,-1 , 0
       0      .1       0   41.39     .06       0  142.26      .1       0
     315    .045       0  351.67     .12       0  458.75      .1       0
Bank Sta=315,351.67
XS Rating Curve= 0 ,0
Exp/Cntr=0.3,0.1

Type RM Length L Ch R = 1 ,9807    ,200,188.7,175.2
XS GIS Cut Line= 3
2369369.90913613576320.8287193032369559.14497814576027.425762817
2369585.18692081575924.995193392
#Sta/Elev= 30
       0 2779.11   15.87 2775.03   35.71 2772.14   39.67 2770.12   43.64 2766.32
   51.58 2755.41   63.48 2732.21   67.45 2725.26   71.41 2720.13   75.38 2716.46
   91.25 2707.86   95.22 2704.94  108.65 2692.01  115.06  2685.3   158.7 2653.71
  166.63 2649.02   182.5 2646.74   194.4 2643.21  220.72 2643.12  222.18 2643.13
  234.08 2642.59  249.95 2643.21  269.79 2644.13  289.62 2647.71  313.43 2650.26
  325.33 2656.05  365.85 2665.91  382.62 2670.34  439.17 2687.72  454.82 2694.34
#Mann= 7 ,-1 , 0
       0     .06       0  108.65      .1       0  220.72      .1       0
  222.18    .045       0  249.95      .1       0  365.85     .12       0
  382.62      .1       0
Bank Sta=222.18,249.95
XS Rating Curve= 0 ,0
Exp/Cntr=0.3,0.1

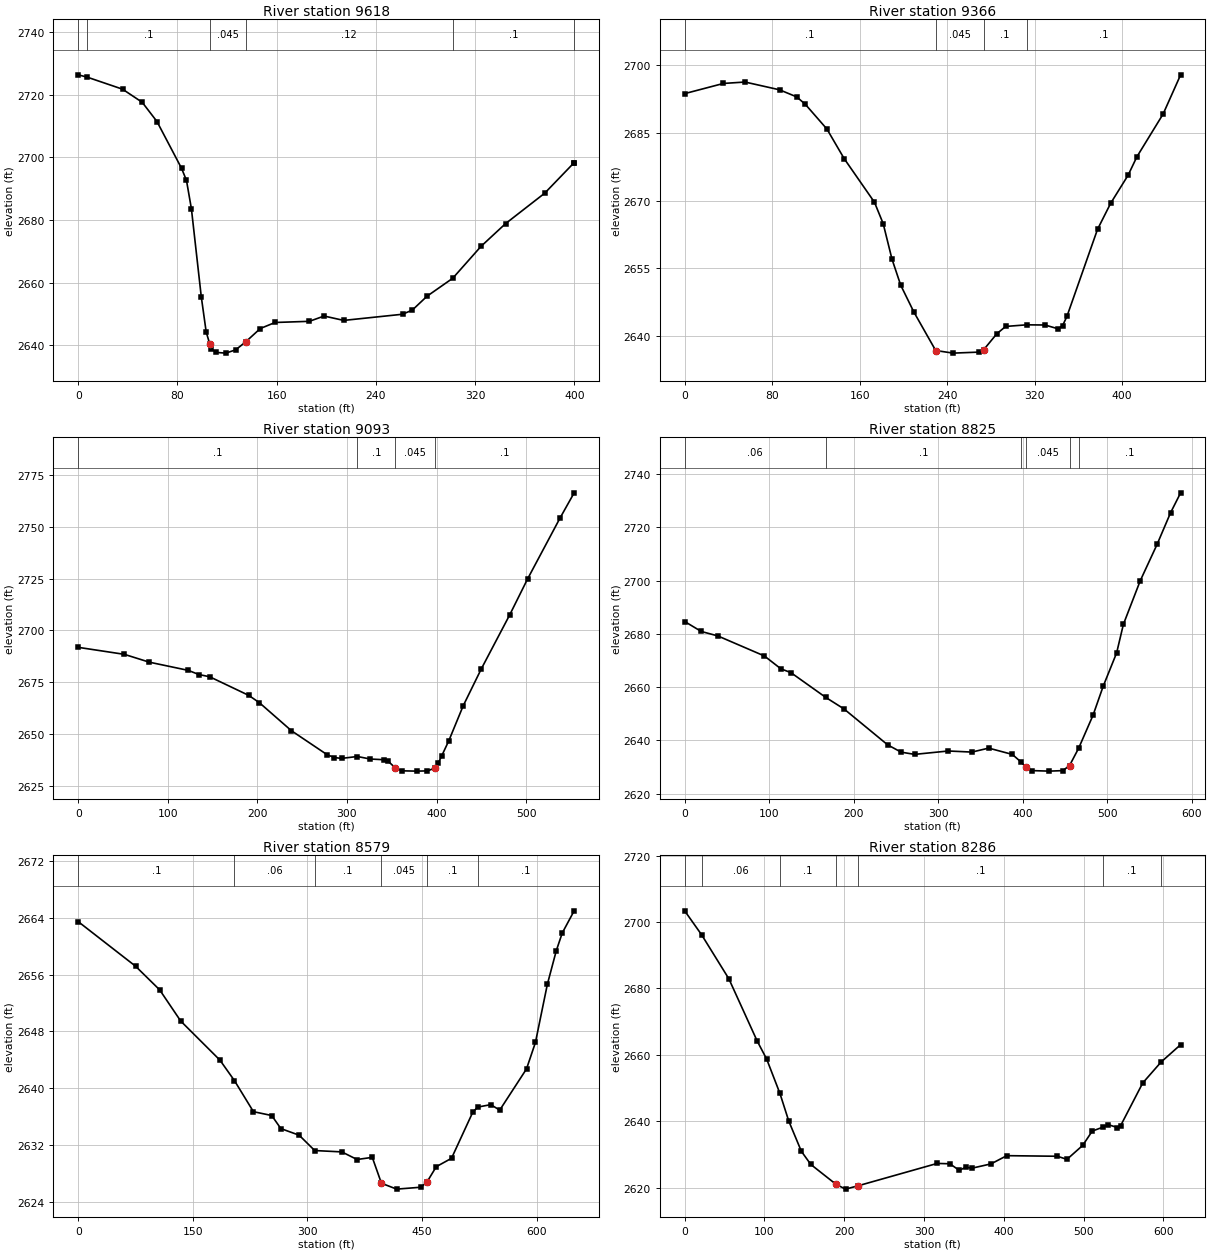
Type RM Length L Ch R = 1 ,9618    ,252.2,251.6,248.3
XS GIS Cut Line= 3
2369701.50624198576293.0508877342369652.89511871 576142.00919506
2369604.28399546575905.898118734
#Sta/Elev= 30
       0 2726.36    7.22 2725.62    35.7 2721.78   51.57 2717.59   63.47 2711.45
    83.3 2696.49   87.27 2692.62   91.24 2683.56   99.17 2655.54  103.14 2644.23
  105.97 2640.44   107.1 2638.92  111.07 2637.69     119 2637.46  126.94 2638.52
  134.87 2641.02  146.77 2645.32  158.67 2647.25  186.33 2647.62  198.19 2649.31
     214 2647.91  261.42 2649.88  269.32 2651.22  281.18 2655.65  301.84 2661.37
  324.65 2671.56  344.41 2678.82  376.02 2688.56  399.48 2698.21  399.73 2698.29
#Mann= 6 ,-1 , 0
       0     .06       0    7.22      .1       0  105.97    .045       0
  134.87     .12       0  301.84      .1       0  399.48     .12       0
Bank Sta=105.97,134.87
XS Rating Curve= 0 ,0
Exp/Cntr=0.3,0.1

Type RM Length L Ch R = 1 ,9366    ,255.8,273.5,302.9
XS GIS Cut Line= 3
2369916.78402664576261.800950229 2369902.8949468 576096.87050581
2369757.06190513575848.606566638
#Sta/Elev= 30
       0 2693.73   35.47 2695.99   55.17  2696.3    86.7 2694.58  102.46    2693
  110.34 2691.35  130.05 2685.87  145.81 2679.31  173.51 2669.63  181.51 2664.87
  189.51 2657.03  197.51 2651.23   209.5 2645.29   229.5 2636.73  245.43 2636.15
  269.49 2636.38  273.49 2636.94  285.48 2640.47  293.48 2642.07  312.64 2642.43
  329.47 2642.39  341.47 2641.54  345.47 2642.23  349.47 2644.28  377.46 2663.62
  389.46 2669.39  405.45 2675.64  413.45 2679.71  437.45 2689.21  453.44  2697.9
#Mann= 4 ,-1 , 0
       0      .1       0   229.5    .045       0  273.49      .1       0
  312.64      .1       0
Bank Sta=229.5,273.49
XS Rating Curve= 0 ,0
Exp/Cntr=0.3,0.1

Type RM Length L Ch R = 1 ,9093    ,263.2,268.3,280.9
XS GIS Cut Line= 3
2369913.31192072576289.5787818132370022.68670197576105.550934643
2370204.97833213575819.092518061
#Sta/Elev= 30
       0 2691.83   51.54 2688.45   79.29 2684.69   122.9 2680.72  134.79 2678.71
  146.68 2677.66  190.29 2668.69  202.18 2665.17  238.04 2651.63  277.99 2640.04
  285.98  2638.7  293.97  2638.3  311.63 2639.21  325.93    2638   341.9 2637.64
   345.9 2636.97  353.89 2633.75  361.88  2632.3  377.86 2632.16  389.84 2632.27
  397.83 2633.57  401.82 2635.96  405.82 2639.55  413.81 2646.92  429.79 2663.68
  449.76 2681.27  481.72 2707.52  501.69 2724.85  537.64 2753.99  553.62 2766.31
#Mann= 4 ,-1 , 0
       0      .1       0  311.63      .1       0  353.89    .045       0
  397.83      .1       0
Bank Sta=353.89,397.83
XS Rating Curve= 0 ,0
Exp/Cntr=0.3,0.1

Type RM Length L Ch R = 1 ,8825    ,245.3,246,248.7
XS GIS Cut Line= 3
2369911.57570373576423.2592887282370074.76993114576313.884179398
2370399.42282514 576096.87050581
#Sta/Elev= 30
       0 2684.63   19.65 2680.89   39.29 2679.21    94.3  2671.7  113.94 2666.85
  125.73 2665.44  166.95 2656.14   188.6  2651.8  240.29 2638.31  256.23 2635.58
  272.17 2634.75  312.01 2636.02  339.91 2635.61  359.83  2637.1  387.72 2634.74
  398.29 2631.83  403.66    2630  411.63 2628.65  431.56 2628.46   447.5 2628.65
  455.47 2630.53   466.3 2637.08  483.36 2649.49  495.31 2660.32  511.25 2672.87
  519.22 2683.56  539.14 2699.91  559.07 2713.56  575.01 2725.43  586.96 2732.94
#Mann= 6 ,-1 , 0
       0     .06       0  166.95      .1       0  398.29      .1       0
  403.66    .045       0  455.47      .1       0   466.3      .1       0
Bank Sta=403.66,455.47
XS Rating Curve= 0 ,0
Exp/Cntr=0.3,0.1

Type RM Length L Ch R = 1 ,8579    ,307.5,292.9,282
XS GIS Cut Line= 4
2369960.18682697576579.5093043152370145.95056306576525.689858139
2370434.14519663576371.1760595592370507.06171747576265.273056149
#Sta/Elev= 30
       0 2663.46   74.99 2657.19  106.57 2653.86   134.2 2649.46  185.51 2643.96
  204.46 2641.08  229.29 2636.71  253.22 2636.17  265.18 2634.33  289.11  2633.4
  309.49 2631.24  344.94 2631.05  364.88 2629.98  384.82 2630.28  396.78 2626.64
  416.72 2625.81  448.62 2626.08   456.6 2626.85  468.56 2628.97   488.5 2630.15
  516.42 2636.66  522.91 2637.36  539.89  2637.7  551.58 2636.93  586.64 2642.73
  598.33 2646.46  613.92 2654.64  625.61 2659.37   633.4 2661.86  648.98 2664.98
#Mann= 6 ,-1 , 0
       0      .1       0  204.46     .06       0  309.49      .1       0
  396.78    .045       0   456.6      .1       0  522.91      .1       0
Bank Sta=396.78,456.6
XS Rating Curve= 0 ,0
Exp/Cntr=0.3,0.1

Type RM Length L Ch R = 1 ,8286    ,290.2,283.5,282.8
XS GIS Cut Line= 4
2370461.92302822576879.856472641 2370451.5060543 576635.06463939
2370487.96464281576379.8564883922370529.63122614576268.745490149
#Sta/Elev= 30
       0 2703.36   21.23 2696.14   55.33  2682.9   90.89 2664.12  102.75  2658.7
  119.37 2648.35  130.41 2640.05  146.22 2630.92  158.07 2626.96  189.69 2620.97
  201.54 2619.53  217.35 2620.54   316.4 2627.27  332.27 2627.17  344.17 2625.18
   352.1 2626.12  360.03 2625.84  383.83 2627.13  403.66 2629.61  467.12 2629.43
  479.02 2628.49  498.85 2632.72  510.72 2637.01  524.23 2638.21   530.5 2638.97
  542.37 2638.07  546.32 2638.65  574.01 2651.51  597.05 2657.82  621.48 2663.04
#Mann= 7 ,-1 , 0
       0      .1       0   21.23     .06       0  119.37      .1       0
  189.69    .045       0  217.35      .1       0  524.23      .1       0
  597.05      .1       0
Bank Sta=189.69,217.35
XS Rating Curve= 0 ,0
Exp/Cntr=0.3,0.1

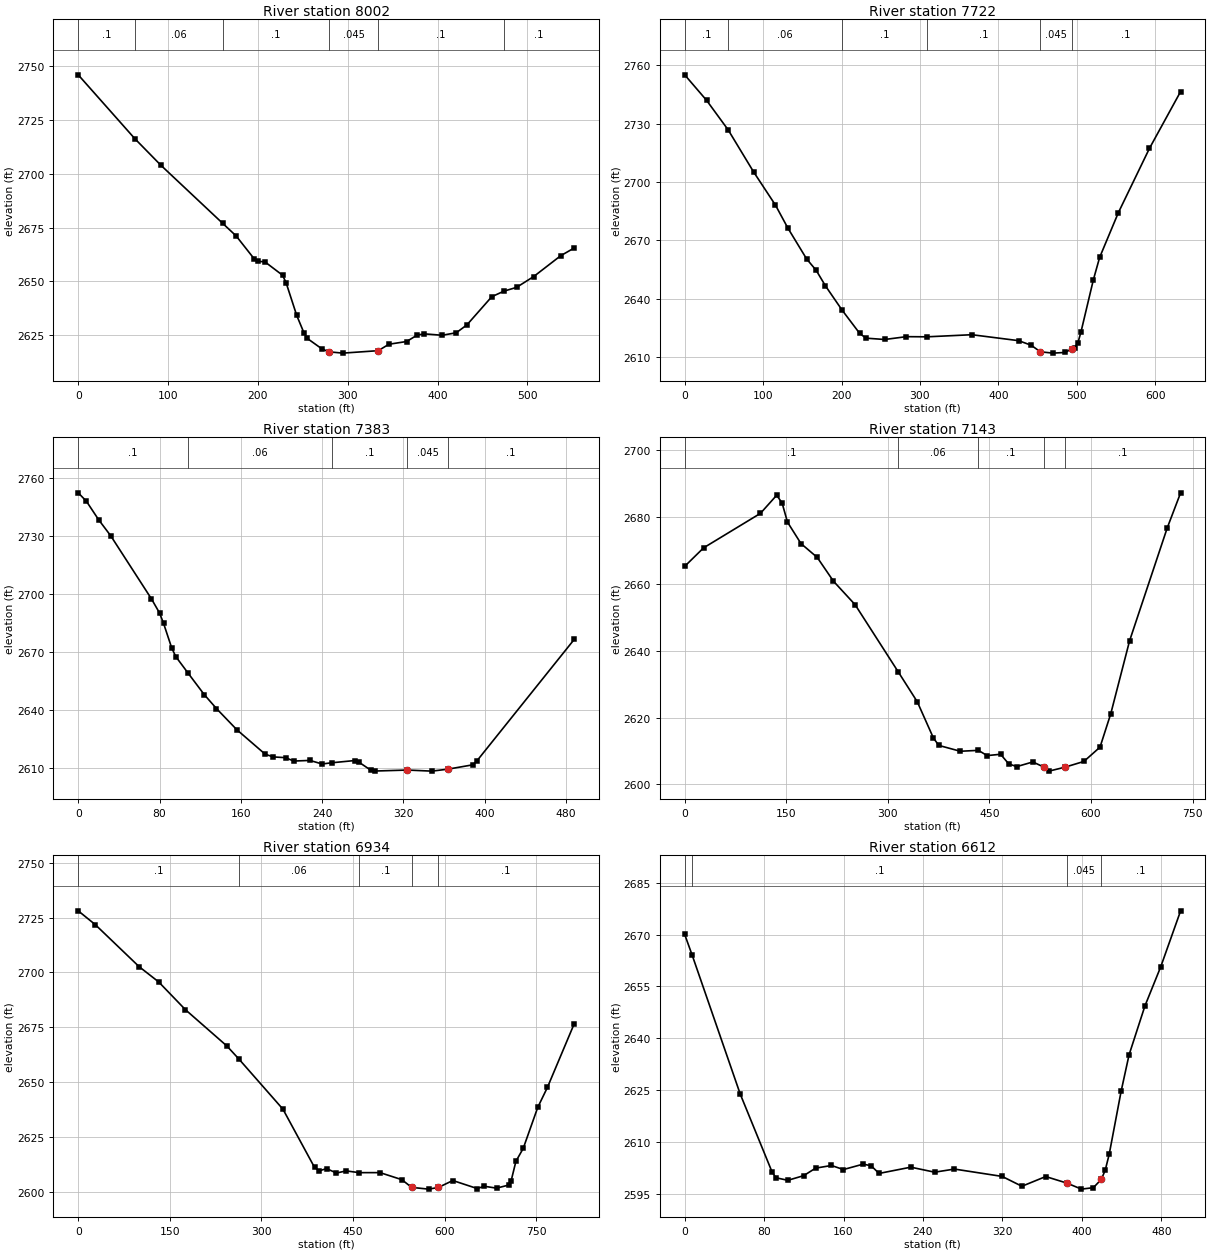
Type RM Length L Ch R = 1 ,8002    ,270.5,280.8,298.5
XS GIS Cut Line= 4
2370768.12648405576775.708715066 2370719.5153608576577.791788056
2370568.47366814576327.7919599712370559.79291122576272.236296818
#Sta/Elev= 30
       0 2745.82   62.98 2716.23   91.91 2703.93  160.88 2676.92  175.83  2671.1
  195.81 2660.53   199.8  2659.3  207.75 2659.12  227.48 2652.88  231.43 2649.39
  243.27 2634.21  251.16 2626.31  255.11 2623.54   270.9 2618.84  278.79 2617.37
  294.58 2616.75  334.05 2617.89  345.89 2620.87  365.63 2622.14  377.47 2625.14
  385.37 2625.69   405.1 2625.03  420.89  2626.2  432.73 2629.85  460.36  2642.9
  473.82 2645.48  487.99 2647.25  507.13 2652.28  537.12 2661.92  552.11  2665.5
#Mann= 6 ,-1 , 0
       0      .1       0   62.98     .06       0  160.88      .1       0
  278.79    .045       0  334.05      .1       0  473.82      .1       0
Bank Sta=278.79,334.05
XS Rating Curve= 0 ,0
Exp/Cntr=0.3,0.1

Type RM Length L Ch R = 1 ,7722    ,333.8,338.1,350.5
XS GIS Cut Line= 3
 2370782.0152358576798.2778956442370825.41803613576628.139128312
2370931.32071146576183.694807231
#Sta/Elev= 30
       0 2755.09   27.93 2741.97   55.48 2726.76   87.79 2705.23  115.73 2688.11
  131.69 2676.21  155.63 2660.33  167.61 2654.61  179.56 2646.53  200.71  2634.1
  223.26 2622.07  231.21 2619.66  255.05 2618.97  282.86 2620.43  309.22 2620.35
  366.29 2621.43  425.88 2618.37  441.77 2616.04  453.69 2612.64  469.58 2611.96
  485.48 2612.31  493.42 2614.17   497.4 2614.84  501.37 2617.14  505.34 2622.76
  521.23 2649.73  529.18 2661.17  553.02 2684.16  592.75 2717.29  632.47 2746.49
#Mann= 6 ,-1 , 0
       0      .1       0   55.48     .06       0  200.71      .1       0
  309.22      .1       0  453.69    .045       0  493.42      .1       0
Bank Sta=453.69,493.42
XS Rating Curve= 0 ,0
Exp/Cntr=0.3,0.1

Type RM Length L Ch R = 1 ,7383    ,244.4,240,236.4
XS GIS Cut Line= 2
 2370910.4874198576864.2502046382371207.36248222576477.097435638
#Sta/Elev= 30
       0 2752.39       8 2748.07   19.99 2738.52   31.99 2730.12   71.98 2697.49
   79.98 2690.15   83.98 2684.72   91.98 2671.99   95.98 2667.52  107.97 2659.03
  123.97 2647.83  135.97 2640.61  155.96 2629.66  183.95 2616.92  191.95 2615.52
  203.95 2615.14  211.95 2613.38  227.94 2613.71  239.94 2611.86  249.19 2612.48
  271.93 2613.64  275.93 2612.88  287.93 2608.61  291.93 2608.21  323.92 2608.72
  347.91 2608.16  363.91  2609.2   387.9  2611.4   391.9 2613.27  487.88 2676.38
#Mann= 5 ,-1 , 0
       0      .1       0  107.97     .06       0  249.19      .1       0
  323.92    .045       0  363.91      .1       0
Bank Sta=323.92,363.91
XS Rating Curve= 0 ,0
Exp/Cntr=0.3,0.1

Type RM Length L Ch R = 1 ,7143    ,215.7,209,204.7
XS GIS Cut Line= 3
2371040.69582081577197.583527476 2371233.4040968576918.069650814
2371387.91789539576556.958496392
#Sta/Elev= 30
       0 2665.27   27.96 2670.82  111.84 2681.14   135.8 2686.56  143.79 2684.28
  151.78 2678.52  171.75 2672.09  195.72 2667.95  219.68 2660.83  251.63  2653.8
  315.15 2633.74  343.47 2624.72  367.28 2613.87  375.21 2611.66  406.95 2609.91
  433.65 2610.18  446.63 2608.61  466.47 2609.01  478.37 2606.15  490.27 2605.31
  514.08 2606.71  529.95 2605.21  537.88 2603.96  561.68 2605.15  589.46 2606.86
  613.26 2611.14  629.13 2621.14   656.9 2642.97  712.45 2676.75  732.28 2687.29
#Mann= 5 ,-1 , 0
       0      .1       0  315.15     .06       0  433.65      .1       0
  529.95    .045       0  561.68      .1       0
Bank Sta=529.95,561.68
XS Rating Curve= 0 ,0
Exp/Cntr=0.3,0.1

Type RM Length L Ch R = 1 ,6934    ,345.4,322,311.6
XS GIS Cut Line= 3
2371356.66795789 577327.79192847 2371490.3484648576994.458605647
2371544.16791096576544.805961639
#Sta/Elev= 30
       0 2728.13   27.93 2721.83   99.76 2702.64  131.68  2695.7  175.58    2683
  243.42 2666.45  262.75  2660.6   335.2 2637.61  386.95 2611.03  394.89 2609.51
  406.81  2610.5   422.7 2608.46  438.59 2609.45  460.15 2608.65   494.2 2608.66
  529.96 2605.44  545.85 2601.93  573.65 2601.13  589.54 2601.88  613.38 2605.06
   653.1 2601.41  665.02 2602.43  684.88 2601.58  704.75 2602.98  708.72  2604.8
  716.66 2613.83  728.58  2619.7  752.41 2638.44   768.3  2647.6     812 2676.53
#Mann= 5 ,-1 , 0
       0      .1       0  262.75     .06       0  460.15      .1       0
  545.85    .045       0  589.54      .1       0
Bank Sta=545.85,589.54
XS Rating Curve= 0 ,0
Exp/Cntr=0.3,0.1

Type RM Length L Ch R = 1 ,6612    ,187.8,185.1,182.3
XS GIS Cut Line= 2
2371851.45961922576945.8474823982371613.61232589 576506.61148423
#Sta/Elev= 30
       0 2670.06    7.61 2664.01   55.94 2623.89   87.91 2601.42   91.91 2599.68
   103.9 2598.94  119.88 2600.29  131.87 2602.46  147.85 2603.23  159.84 2602.05
  179.82 2603.62  187.81 2603.14   195.8 2600.93  227.77 2602.74  251.75 2601.29
  271.73 2602.19  319.68 2600.07  339.66 2597.22  363.64 2600.03  385.09 2598.12
   399.6 2596.39  411.59 2596.81  419.58 2599.19  423.58 2601.88  427.57 2606.47
  439.56 2624.67  447.55  2635.2  463.54 2649.36  479.52 2660.73   499.5 2676.88
#Mann= 4 ,-1 , 0
       0     .06       0    7.61      .1       0  385.09    .045       0
  419.58      .1       0
Bank Sta=385.09,419.58
XS Rating Curve= 0 ,0
Exp/Cntr=0.3,0.1

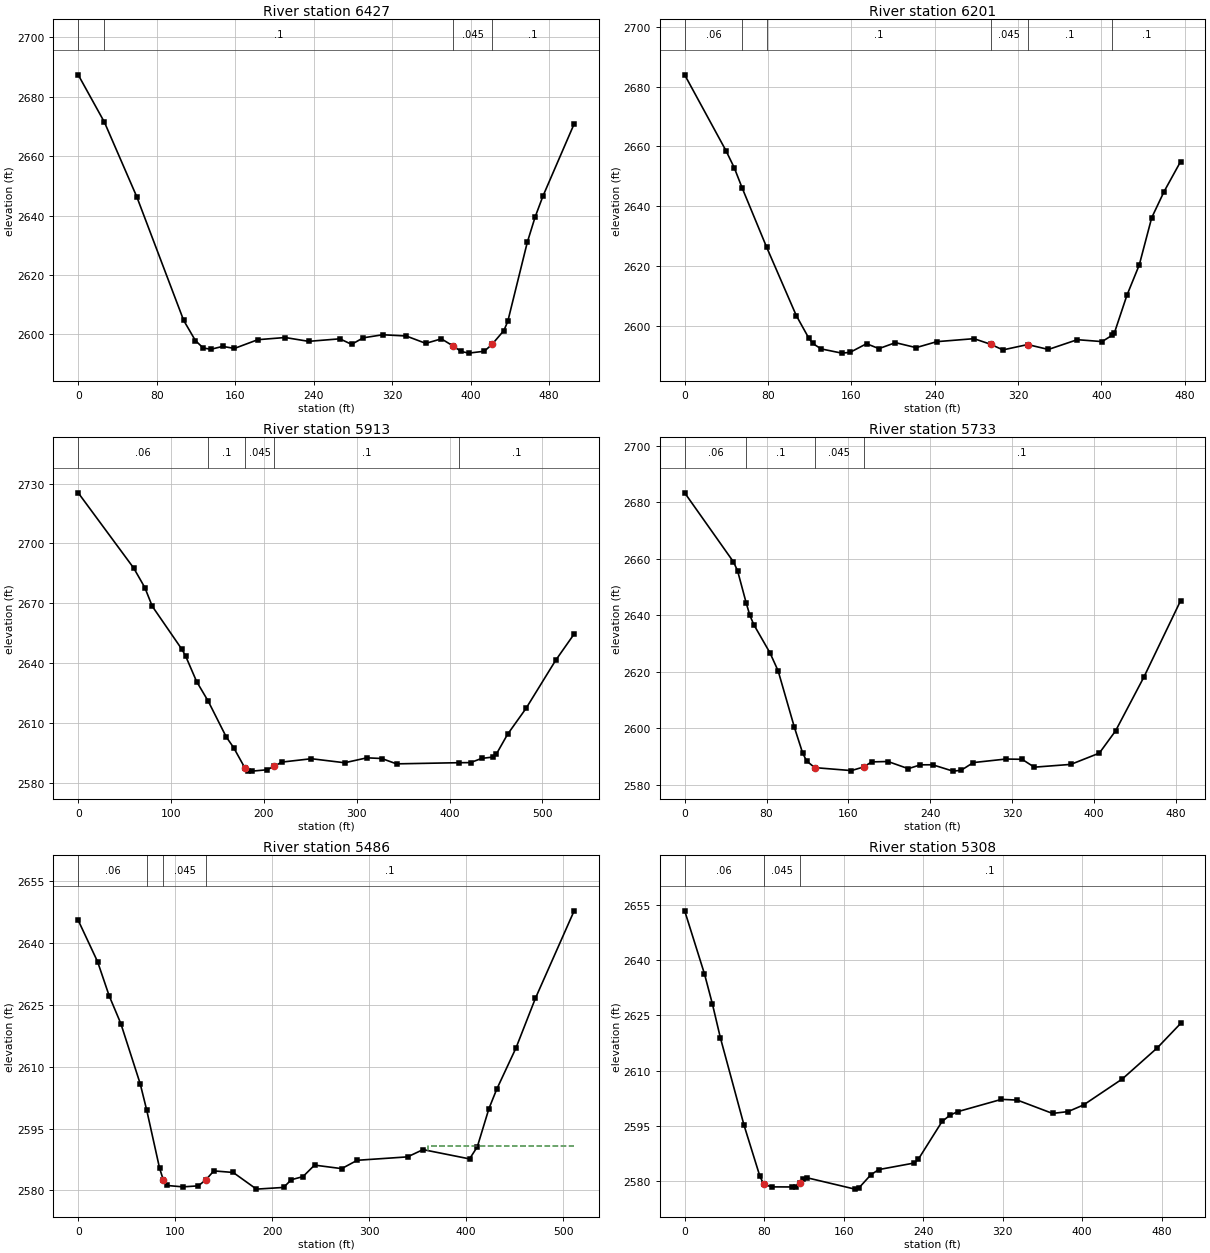
Type RM Length L Ch R = 1 ,6427    ,227.7,226.7,227.9
XS GIS Cut Line= 2
2372061.52908097576831.2640501412371762.91812964576423.277989477
#Sta/Elev= 30
       0 2687.41   26.73 2671.44   59.72 2646.31  107.49 2604.68  119.43 2597.89
  127.39 2595.37  135.35 2594.94   147.3 2595.91  159.24 2595.22  183.13 2598.17
  210.99  2598.9  234.88 2597.61  266.73 2598.46  278.67  2596.6  290.61  2598.8
  310.52 2599.83  334.41 2599.41  354.31 2596.93  370.24 2598.45  382.18 2596.05
  390.14 2594.23   398.1 2593.64  414.03 2594.28  421.99 2596.63  433.93 2601.25
  437.91 2604.32  457.82 2630.98  465.78 2639.48  473.74 2646.52  505.59 2670.88
#Mann= 4 ,-1 , 0
       0     .06       0   26.73      .1       0  382.18    .045       0
  421.99      .1       0
Bank Sta=382.18,421.99
XS Rating Curve= 0 ,0
Exp/Cntr=0.3,0.1

Type RM Length L Ch R = 1 ,6201    ,287.2,287.1,281.6
XS GIS Cut Line= 2
2372216.04287955576655.9169598972371929.58479105576275.708730817
#Sta/Elev= 30
       0 2683.99   39.67 2658.57    47.6 2652.87   55.16 2646.12   78.56 2626.36
  107.11 2603.39  119.01  2595.9  122.98 2594.03  130.91 2592.22  150.75  2590.8
  158.68 2591.05  174.55 2593.95  186.45 2592.31  202.32 2594.31  222.15 2592.64
  241.99 2594.64  277.69 2595.64  293.56 2593.78  305.46 2591.88  329.26 2593.67
   349.1 2592.03  376.87  2595.3  400.67 2594.66  410.42 2596.81  412.57 2597.67
  424.47 2610.15  436.37 2620.36  448.27 2636.13  460.17 2644.91  476.04 2654.96
#Mann= 6 ,-1 , 0
       0     .06       0   55.16      .1       0   78.56      .1       0
  293.56    .045       0  329.26      .1       0  410.42      .1       0
Bank Sta=293.56,329.26
XS Rating Curve= 0 ,0
Exp/Cntr=0.3,0.1

Type RM Length L Ch R = 1 ,5913    ,181.7,180.6,179.5
XS GIS Cut Line= 2
2372453.89017288576463.2086838932372040.69578931576124.667038143
#Sta/Elev= 30
       0 2725.35    59.8 2687.66   71.75 2677.92   79.73 2668.58  111.62 2647.04
   115.6 2643.73  127.56 2630.84  140.02 2621.03  159.45 2603.12  167.43 2597.77
  179.39 2587.71  183.37 2586.13  187.36 2586.01   203.3 2586.68  211.28  2588.5
  219.25 2590.53  251.14 2592.22  287.02  2590.2  310.94 2592.67  326.88 2592.33
  342.83 2589.65  410.01 2590.23  422.55 2590.27  434.51 2592.38  446.47 2593.04
  450.46  2594.6  462.42 2604.43  482.35 2617.43  514.24 2641.48  534.17 2654.67
#Mann= 5 ,-1 , 0
       0     .06       0  140.02      .1       0  179.39    .045       0
  211.28      .1       0  410.01      .1       0
Bank Sta=179.39,211.28
XS Rating Curve= 0 ,0
Exp/Cntr=0.3,0.1

Type RM Length L Ch R = 1 ,5733    ,248.7,247.3,246
XS GIS Cut Line= 2
2372533.75123364576282.6529426432372137.91803581576003.139065981
#Sta/Elev= 30
       0 2683.41   47.66 2658.94   51.64 2655.84   60.12 2644.37   63.55 2640.14
   67.52 2636.71   83.41 2626.66   91.35 2620.29  107.24 2600.27  115.19 2591.28
  119.16 2588.38   127.1 2586.04  162.85 2584.99  174.76 2586.26  182.71 2588.07
   198.6 2588.21  218.46 2585.67  230.37 2587.03  242.29 2587.05  262.15  2584.8
  270.09 2585.09  282.01 2587.83  313.78 2589.08  329.67 2588.99  341.59  2586.2
  377.33 2587.19  405.14 2591.18  421.02 2599.07  448.83 2618.23  484.57  2645.2
#Mann= 4 ,-1 , 0
       0     .06       0   60.12      .1       0   127.1    .045       0
  174.76      .1       0
Bank Sta=127.1,174.76
XS Rating Curve= 0 ,0
Exp/Cntr=0.3,0.1

Type RM Length L Ch R = 1 ,5486    ,177.5,178,178.4
XS GIS Cut Line= 2
2372667.43174055576067.3751579822372226.45952539 575808.69457297
#Sta/Elev= 30
       0 2645.48   19.97 2635.45   31.95 2627.15   43.94 2620.44   63.91 2605.84
   70.63 2599.45   83.88 2585.37   87.87 2582.46   91.86 2581.19  107.84 2580.86
  123.82  2581.1  131.81 2582.62  139.79 2584.73  159.76 2584.35  183.73 2580.31
  211.69 2580.72  219.68 2582.59  231.66 2583.34  243.64 2586.13   271.6 2585.28
  287.58  2587.3   339.5 2588.13  355.48 2589.89  403.41 2587.64  411.39 2590.55
  423.38 2599.82  431.36 2604.49  451.33 2614.56  471.31 2626.57  511.25 2647.78
#Mann= 4 ,-1 , 0
       0     .06       0   70.63      .1       0   87.87    .045       0
  131.81      .1       0
#XS Ineff= 2 , 0
                          360.88         2590.82
Permanent Ineff=
       F       F
Bank Sta=87.87,131.81
XS Rating Curve= 0 ,0
Exp/Cntr=0.3,0.1

Type RM Length L Ch R = 1 ,5308    ,232.3,236.6,237.3
XS GIS Cut Line= 3
2372733.40404956575905.9168194832372441.19137938575719.112731144
2372320.20966597575626.402942806
#Sta/Elev= 30
       0 2653.39   19.93 2636.25   27.91 2628.08   35.88 2618.96    59.8  2595.1
   75.74 2581.24   79.73 2579.05    87.7 2578.39  107.63 2578.37  111.62 2578.43
  115.61 2579.35  119.59  2580.5  123.58 2580.84  171.42 2577.78   175.4 2578.11
  187.36 2581.66  195.34 2583.09  231.21 2584.88   235.2  2585.9  259.12 2596.16
  267.09 2597.87  275.06 2598.84  318.91 2602.17  334.86 2601.97  370.27 2598.35
   385.9 2598.84  401.53 2600.65  440.62 2607.73  475.79 2616.17  499.24 2622.79
#Mann= 3 ,-1 , 0
       0     .06       0   79.73    .045       0  115.61      .1       0
Bank Sta=79.73,115.61
XS Rating Curve= 0 ,0
Exp/Cntr=0.3,0.1

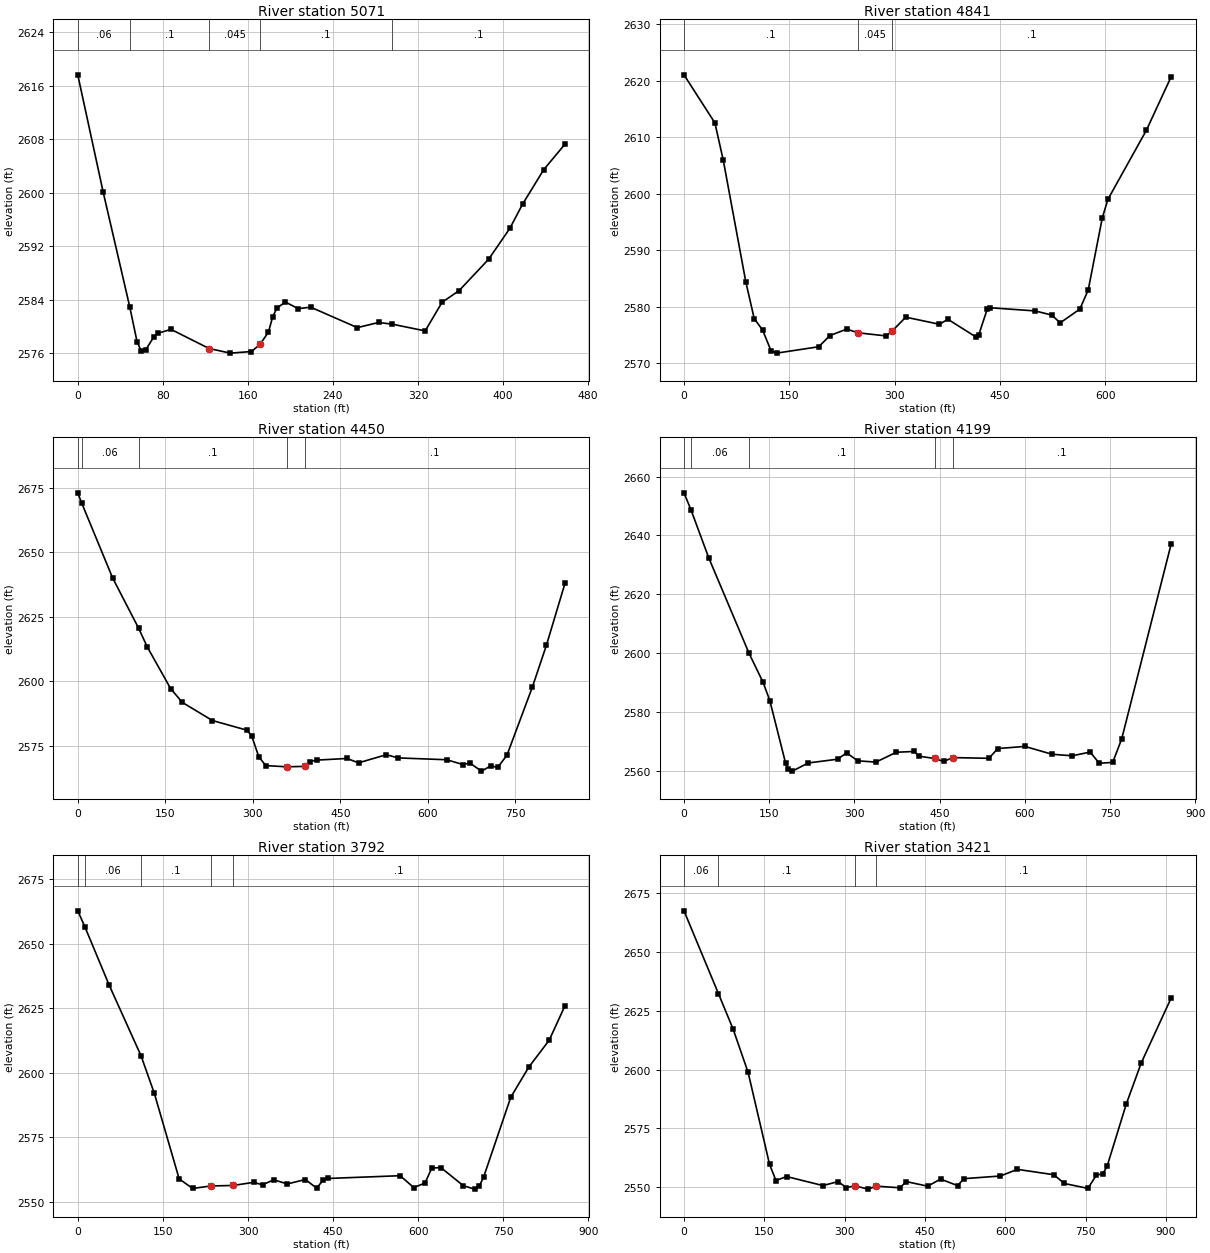
Type RM Length L Ch R = 1 ,5071    ,225,229.8,223.4
XS GIS Cut Line= 2
 2372847.9874818575734.0418351442372486.76412289575452.185771555
#Sta/Elev= 30
       0 2617.61    23.9 2600.08   48.85 2582.96   55.78 2577.72   59.76 2576.31
   63.75 2576.49   71.71  2578.5    75.7 2579.01   87.65 2579.58  123.51 2576.72
  143.43 2576.03  163.35 2576.27  171.32 2577.32  179.29 2579.16  183.27 2581.44
  187.25 2582.76  195.22 2583.67  207.18 2582.68  219.13 2582.89  262.95 2579.84
  282.87 2580.61  295.94 2580.35   326.7 2579.35  342.64 2583.63  358.57 2585.36
  386.46 2590.07  406.38 2594.68  418.33 2598.29  438.26 2603.45  458.18 2607.25
#Mann= 5 ,-1 , 0
       0     .06       0   48.85      .1       0  123.51    .045       0
  171.32      .1       0  295.94      .1       0
Bank Sta=123.51,171.32
XS Rating Curve= 0 ,0
Exp/Cntr=0.3,0.1

Type RM Length L Ch R = 1 ,4841    ,382,391,411.7
XS GIS Cut Line= 3
2373091.04309805575659.3890973032372627.82322396 575272.06408456
 2372558.0569593575214.944776222
#Sta/Elev= 30
       0 2621.05   43.99 2612.54   55.98  2605.9   87.97 2584.42   99.97 2577.88
  111.97 2575.83  123.96 2572.18  131.96 2571.75  191.94 2572.88  207.94 2574.87
  231.93 2576.01  247.92 2575.35  287.91  2574.8  295.91 2575.59   315.9 2578.12
  363.89 2576.86  375.89 2577.75  415.87 2574.61  419.87 2574.97  431.87 2579.52
  435.87 2579.79  499.85 2579.23  523.84  2578.5  535.84 2577.11  563.83 2579.55
  575.82 2582.94  595.82 2595.69  603.82 2598.98   658.7 2611.24  693.98 2620.72
#Mann= 3 ,-1 , 0
       0      .1       0  247.92    .045       0  295.91      .1       0
Bank Sta=247.92,295.91
XS Rating Curve= 0 ,0
Exp/Cntr=0.3,0.1

Type RM Length L Ch R = 1 ,4450    ,256,251.4,248.3
XS GIS Cut Line= 3
 2373333.1184013575727.7931599772373272.35441522575447.845229059
2373155.16698556574911.821038648
#Sta/Elev= 30
       0 2673.06    6.44 2669.26   59.68 2640.13  104.14 2620.69  119.36 2613.28
  159.15 2597.26  179.04 2591.93  230.76 2584.88  290.44 2581.11  298.39 2578.74
  310.32 2570.83  322.25 2567.42  358.03 2566.96  389.84 2567.12  397.79 2568.99
  409.72 2569.55  461.41 2570.18  481.29 2568.49     529 2571.64  548.88  2570.4
  632.38 2569.69  660.21 2567.84  672.14 2568.41  692.02 2565.28  707.92 2567.29
  719.85 2566.72  735.75 2571.46  779.49 2597.96  803.34 2614.01  835.15 2637.99
#Mann= 5 ,-1 , 0
       0      .1       0    6.44     .06       0  104.14      .1       0
  358.03    .045       0  389.84      .1       0
Bank Sta=358.03,389.84
XS Rating Curve= 0 ,0
Exp/Cntr=0.3,0.1

Type RM Length L Ch R = 1 ,4199    ,405.4,406.8,416.6
XS GIS Cut Line= 3
2373688.58717856575678.0537581442373426.43448764 575146.80383639
2373324.00391822574902.012003139
#Sta/Elev= 30
       0 2654.52   12.45 2648.65   43.74 2632.31  114.67 2599.83  139.16 2590.05
  151.08 2583.81  178.92 2562.47  182.89 2560.62  190.84 2559.79  218.68 2562.57
  270.36 2563.85  286.27 2565.99  306.15 2563.29  337.95 2562.86  373.74 2566.21
  405.54 2566.49  413.49 2564.88  441.33 2564.09  457.23 2563.07  473.13  2564.4
  536.75 2564.15  552.65 2567.48  600.33  2568.2  647.86 2565.54   683.5 2565.01
  715.19 2566.28  731.03 2562.47  754.79 2562.76  770.64 2570.75  857.77 2637.14
#Mann= 5 ,-1 , 0
       0      .1       0   12.45     .06       0  114.67      .1       0
  441.33    .045       0  473.13      .1       0
Bank Sta=441.33,473.13
XS Rating Curve= 0 ,0
Exp/Cntr=0.3,0.1

Type RM Length L Ch R = 1 ,3792    ,368.9,371.1,370.2
XS GIS Cut Line= 3
2373862.63210605575651.8382593992373860.46216288575302.445913553
2373783.20509955574799.147379473
#Sta/Elev= 30
       0 2662.71   12.85 2656.34   55.59  2633.8  111.45 2606.58     135 2591.96
  178.67 2558.89  202.49 2555.17  234.26 2556.14  273.96 2556.34  309.69 2557.54
  325.58  2556.6  345.43 2558.53  369.29 2556.93  401.11 2558.64     421 2555.29
  432.94 2558.56  440.89 2559.05  568.19 2560.12  592.06 2555.53  611.95 2557.28
  623.89 2563.06   639.8 2563.29  679.58 2556.23  699.47 2554.92  707.43 2555.98
  715.38 2559.69  763.12 2590.52  794.94 2602.21  830.75 2612.58  858.59 2625.92
#Mann= 5 ,-1 , 0
       0      .1       0   12.85     .06       0  111.45      .1       0
  234.26    .045       0  273.96      .1       0
Bank Sta=234.26,273.96
XS Rating Curve= 0 ,0
Exp/Cntr=0.3,0.1

Type RM Length L Ch R = 1 ,3421    ,300.2,295.8,283.2
XS GIS Cut Line= 3
2374194.66359422575651.8382593992374188.15310855575252.532955647
2374116.53842239574746.890594229
#Sta/Elev= 30
       0 2667.61   64.32 2632.37   91.85 2617.21  119.81 2598.81  159.74 2559.77
  171.72 2552.83  191.69 2554.51  259.58 2550.67  287.54 2552.35  303.51 2549.82
  319.49 2550.59  343.45 2549.16  359.42 2550.42  403.35 2549.73  415.32 2552.36
  455.21 2550.41  479.15 2553.43  511.07 2550.66  523.04 2553.62  590.87 2554.74
  622.78 2557.57  690.61  2555.3  710.56 2551.56  754.45 2549.47  770.41 2555.13
  782.38 2555.67  790.36 2558.91  826.26 2585.44  854.19  2602.9  910.05 2630.54
#Mann= 4 ,-1 , 0
       0     .06       0   64.32      .1       0  319.49    .045       0
  359.42      .1       0
Bank Sta=319.49,359.42
XS Rating Curve= 0 ,0
Exp/Cntr=0.3,0.1