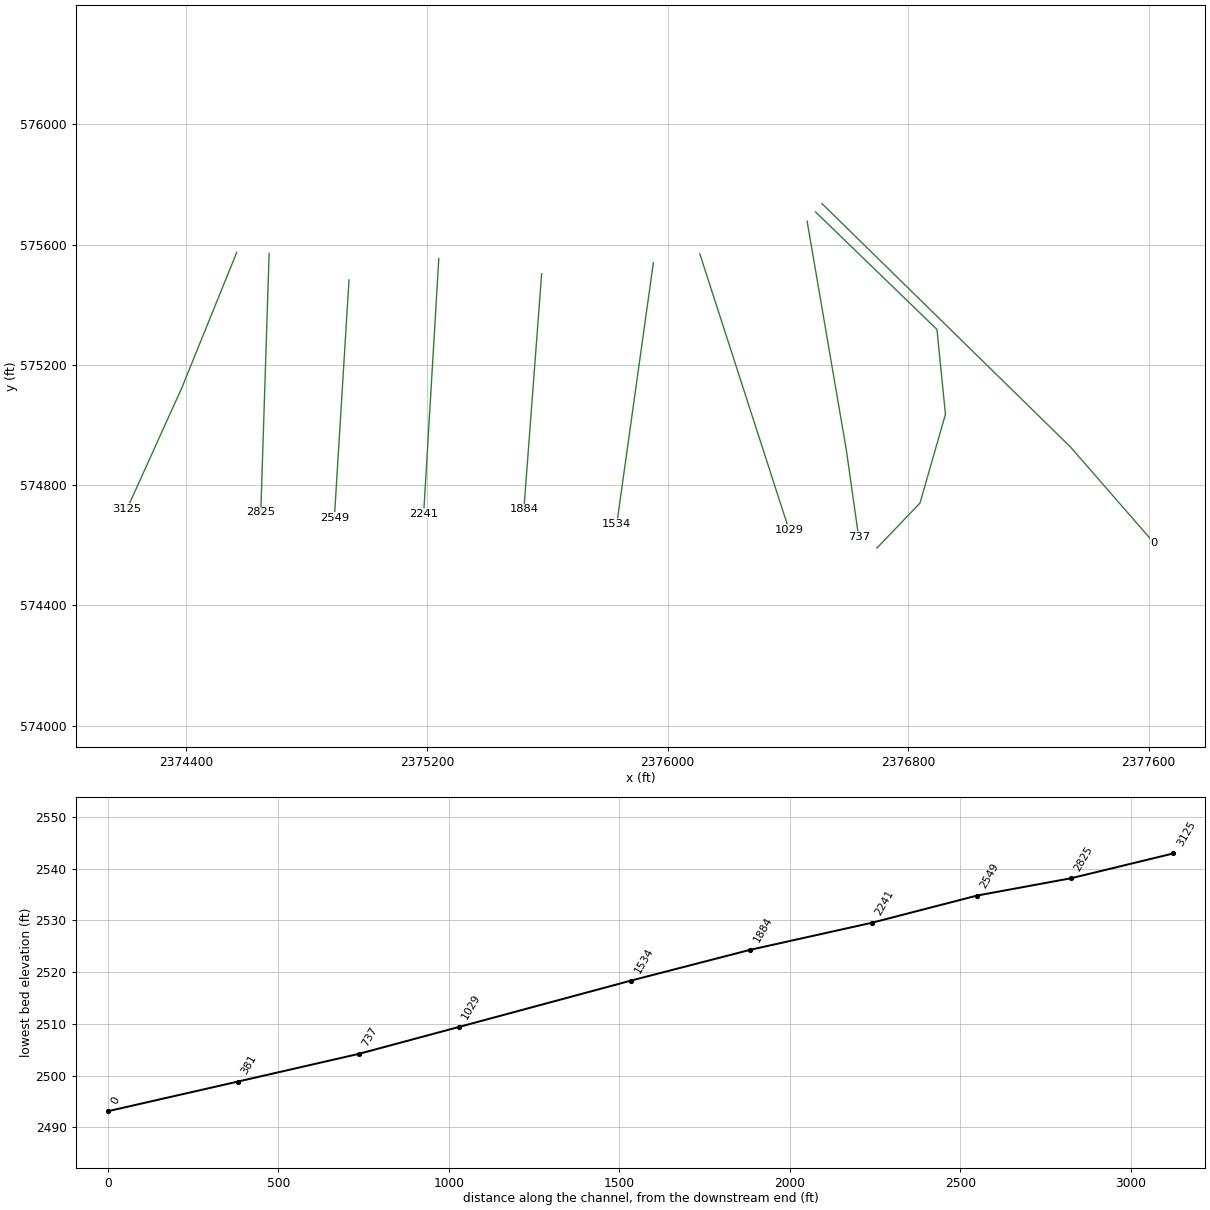
HEC-RAS study LAURELFK.prj: LAURELFK

--- LAURELFK.g01 (geometry) --- (continued)

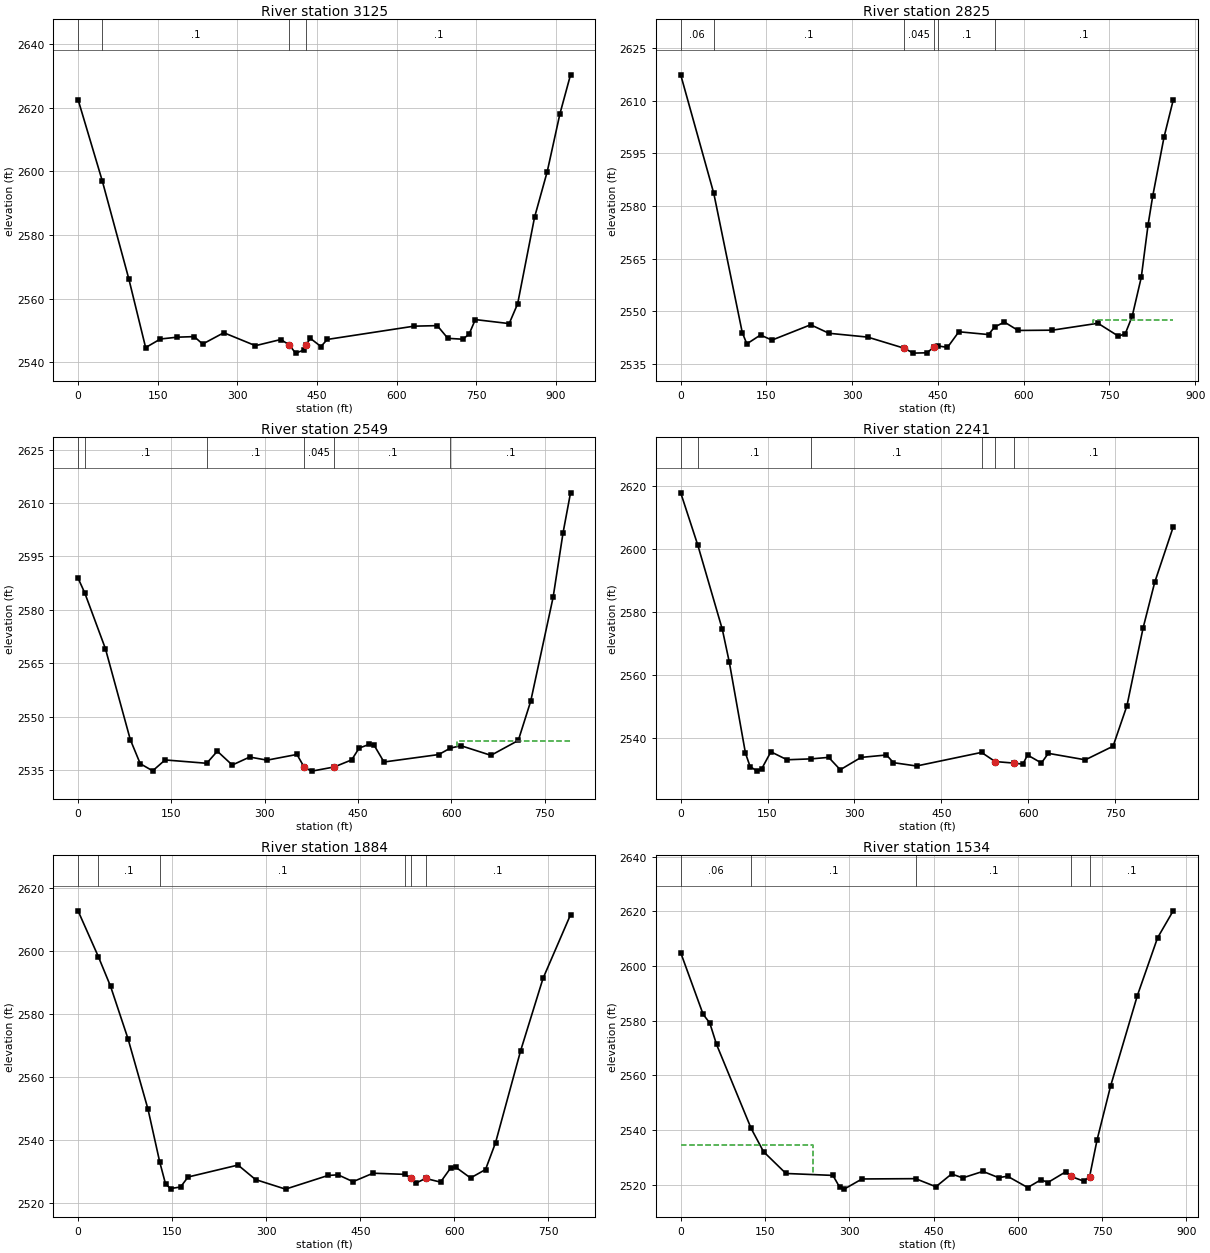
Type RM Length L Ch R = 1 ,3125    ,289.6,299.6,298.4
XS GIS Cut Line= 3
2374567.49322914575574.3210259832374385.20159897575124.668381974
2374202.90996881574721.890644223
#Sta/Elev= 30
       0  2622.6   45.59 2597.06   95.45 2566.35  127.27 2544.66   155.1 2547.36
  186.92 2547.93  218.74 2548.11  234.65 2545.77  274.42 2549.33  334.07 2545.26
   381.8  2547.2   397.7  2545.5  409.64 2542.92  425.54 2543.91  429.52  2545.6
  437.47 2547.55  457.36    2545  469.29 2547.22  632.57 2551.39  676.38 2551.56
   696.3 2547.57  724.18 2547.29  736.12 2548.81  748.07 2553.46   811.8  2552.2
  827.73 2558.42   859.6 2585.62  883.49 2599.98  907.39 2618.14  927.31 2630.36
#Mann= 4 ,-1 , 0
       0     .06       0   45.59      .1       0   397.7    .045       0
  429.52      .1       0
Bank Sta=397.7,429.52
XS Rating Curve= 0 ,0
Exp/Cntr=0.3,0.1

Type RM Length L Ch R = 1 ,2825    ,274.6,276,268.6
XS GIS Cut Line= 2
2374675.13212147575570.8489200622374647.35428989574709.737781391
#Sta/Elev= 30
       0 2617.31   57.91 2583.55  107.69 2543.99  115.67 2540.76   139.6 2543.29
  159.55 2541.83  227.36  2546.2  259.27 2543.78  327.07 2542.69  390.89 2539.53
  406.85 2538.13  430.78 2538.23  442.75 2539.81  450.94 2540.16  466.68 2539.76
  486.62 2544.21  538.47 2543.41   549.2 2545.59   566.4 2546.95  590.33 2544.58
  650.16 2544.66  729.93 2546.63  765.83 2542.94   777.8 2543.68  789.76 2548.57
  805.72 2559.69  817.68 2574.72  825.66 2582.73   845.6 2599.63  861.56  2610.1
#Mann= 6 ,-1 , 0
       0     .06       0   57.91      .1       0  390.89    .045       0
  442.75      .1       0  450.94      .1       0   549.2      .1       0
#XS Ineff= 2 , 0
                          721.88         2547.51
Permanent Ineff=
       F       F
Bank Sta=390.89,442.75
XS Rating Curve= 0 ,0
Exp/Cntr=0.3,0.1

Type RM Length L Ch R = 1 ,2549    ,312.7,308.9,310.4
XS GIS Cut Line= 2
2374940.75724639575482.3071023972374892.14612314574692.376595646
#Sta/Elev= 30
       0 2588.94   10.84 2584.76   43.97 2569.15   83.94 2543.64   99.93 2536.87
  119.91 2534.86   139.9 2537.92  206.73 2536.98  223.84 2540.37  247.82 2536.49
   275.8 2538.73  303.78 2537.86  351.74 2539.46  363.74  2535.8  375.73 2534.78
   411.7 2535.95  439.68 2537.93  451.67 2541.23  467.66 2542.28  475.65 2542.08
  491.64 2537.34  579.58 2539.43  598.53 2541.26  615.55  2541.9  663.52 2539.21
  707.49 2543.39  727.47 2554.42  763.44 2583.55  779.43 2601.67  791.42 2612.86
#Mann= 6 ,-1 , 0
       0     .06       0   10.84      .1       0  206.73      .1       0
  363.74    .045       0   411.7      .1       0  598.53      .1       0
#XS Ineff= 2 , 0
                          608.71         2543.12
Permanent Ineff=
       F       F
Bank Sta=363.74,411.7
XS Rating Curve= 0 ,0
Exp/Cntr=0.3,0.1

Type RM Length L Ch R = 1 ,2241    ,348.5,356.2,350.9
XS GIS Cut Line= 2
2375239.36819772575553.4877343182375189.02118555574704.529458478
#Sta/Elev= 30
       0 2617.97    29.6 2601.29   71.87 2574.57   83.85 2564.21   111.8 2535.24
  119.78 2530.99  131.76 2529.52  139.75 2530.23  155.72 2535.66  183.67 2533.13
  225.54 2533.42  255.53 2533.89   275.5 2529.96  311.43 2533.88  355.35 2534.65
  367.33 2532.21  407.26 2531.15  519.44 2535.47  543.01 2532.56  574.95 2532.08
  590.92 2531.74  598.91 2534.64  622.87 2532.11  634.84 2535.17  698.73 2533.11
  746.64 2537.44   770.6 2550.31  798.54 2575.06  818.51 2589.51  850.45  2607.1
#Mann= 6 ,-1 , 0
       0     .06       0    29.6      .1       0  225.54      .1       0
  519.44      .1       0  543.01    .045       0  574.95      .1       0
Bank Sta=543.01,574.95
XS Rating Curve= 0 ,0
Exp/Cntr=0.3,0.1

Type RM Length L Ch R = 1 ,1884    ,349.4,349.9,347.9
XS GIS Cut Line= 2
2375581.38227747575503.1403940622375522.35450839 574720.15442723
#Sta/Elev= 30
       0 2612.76   32.35 2598.21   51.82 2588.78   79.72 2572.07   111.6 2549.66
  130.18 2532.98   139.5 2525.95  147.48 2524.49  163.42 2524.97  175.38 2528.15
  255.09 2531.95  282.99 2527.34  330.82  2524.3  398.58 2528.64  414.53 2528.85
  438.44 2526.67  470.33 2529.36  521.51 2528.99  530.64 2527.68  538.09 2526.15
  554.03  2527.7  577.95 2526.53  593.89 2530.97  601.86 2531.33  625.77 2527.85
  649.69 2530.53  665.63 2539.04  705.49 2568.18  741.36 2591.28  785.21 2611.51
#Mann= 6 ,-1 , 0
       0     .06       0   32.35      .1       0  130.18      .1       0
  521.51      .1       0  530.64    .045       0  554.03      .1       0
Bank Sta=530.64,554.03
XS Rating Curve= 0 ,0
Exp/Cntr=0.3,0.1

Type RM Length L Ch R = 1 ,1534    ,500.9,505.9,508.6
XS GIS Cut Line= 2
2375952.91007772575539.5989825582375831.38210556574671.543303981
#Sta/Elev= 30
       0 2604.87   39.84 2582.35   51.79 2579.11   63.75 2571.31  125.36 2540.56
  147.41 2532.06  187.26 2524.08  270.92 2523.37  282.88 2519.07  290.85 2518.35
  322.72 2522.07  417.97 2522.18   454.2 2519.23  482.09 2523.89  502.01 2522.47
  537.87 2524.84  565.76 2522.55  581.69 2523.07  617.55 2518.93  641.45  2521.8
  653.41 2520.76  685.28 2524.69   694.7 2522.99  717.15 2521.28  727.67 2522.86
  741.06 2536.38  764.97 2555.97  812.78 2589.19  848.63 2610.28  876.52 2620.19
#Mann= 5 ,-1 , 0
       0     .06       0  125.36      .1       0  417.97      .1       0
   694.7    .045       0  727.67      .1       0
#XS Ineff= 2 , 0
          235.73 2534.47
Permanent Ineff=
       F       F
Bank Sta=694.7,727.67
XS Rating Curve= 0 ,0
Exp/Cntr=0.3,0.1

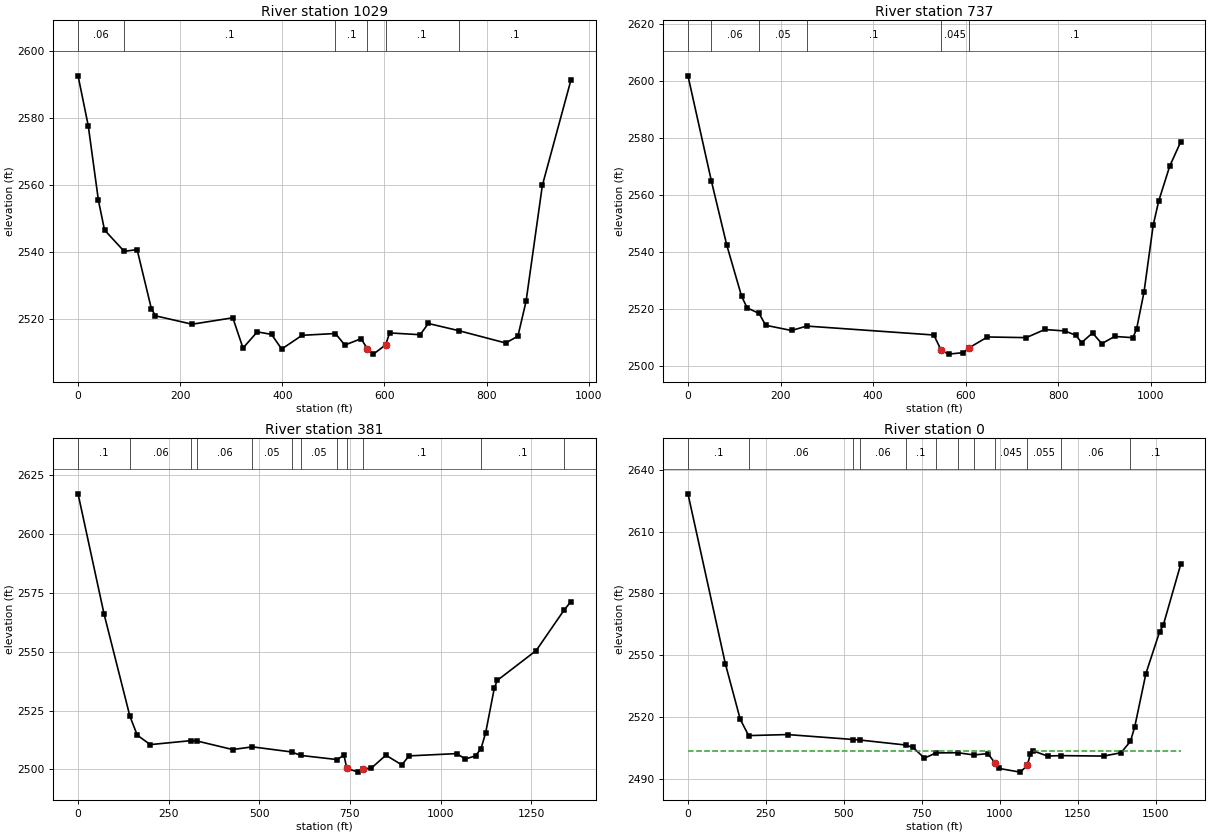
Type RM Length L Ch R = 1 ,1029    ,297.1,292,287.7
XS GIS Cut Line= 2
 2376107.4238763575569.1127030552376404.29893872574650.710012317
#Sta/Elev= 30
       0 2592.63   19.94 2577.72   39.88 2555.36   51.85 2546.49   90.39 2540.12
  115.66 2540.64  143.58 2522.97  151.56 2520.83  223.35 2518.32  303.12 2520.24
  323.06 2511.18  350.98 2516.03   378.9 2515.28  398.84 2510.89  438.72    2515
  504.09 2515.54  522.48 2512.08  554.39 2513.99  566.71 2510.95  578.32 2509.37
  602.25 2512.11  610.23 2515.71  670.05 2515.18  686.01 2518.54  745.67 2516.39
  837.56  2512.7  861.49 2514.75  877.45 2525.17  909.36 2559.86  965.19 2591.29
#Mann= 6 ,-1 , 0
       0     .06       0   90.39      .1       0  504.09      .1       0
  566.71    .045       0  602.25      .1       0  745.67      .1       0
Bank Sta=566.71,602.25
XS Rating Curve= 0 ,0
Exp/Cntr=0.3,0.1

Type RM Length L Ch R = 1 ,737     ,358,355.6,353.1
XS GIS Cut Line= 3
2376464.19481631575678.0537581442376594.40288922574918.505080387
2376635.63574639574627.706449389
#Sta/Elev= 30
       0 2601.72   50.75 2564.74   83.85 2542.37  115.79 2524.49  127.77 2520.41
  153.63 2518.46   167.7 2514.32   223.6 2512.48  256.51 2514.03  531.05  2510.9
  547.03 2505.48     563  2504.2  594.94 2504.73  606.92 2506.39  646.85 2510.21
   730.7 2509.98  770.63 2512.83  814.29 2512.31   838.1 2510.77  850.01 2508.21
  873.82 2511.64  893.67 2507.87  921.45 2510.39  961.14 2509.97  969.08 2513.15
  984.95 2525.95  1004.8 2549.41 1016.71 2557.86 1040.52  2570.1 1064.34 2578.64
#Mann= 6 ,-1 , 0
       0      .1       0   50.75     .06       0  153.63     .05       0
  256.51      .1       0  547.03    .045       0  606.92      .1       0
Bank Sta=547.03,606.92
XS Rating Curve= 0 ,0
Exp/Cntr=0.3,0.1

Type RM Length L Ch R = 1 ,381     ,320.2,381,398.3
XS GIS Cut Line= 5
2376492.40637405575708.435587138 2376896.0522203575317.810712233
2376924.26410614575035.6925100542376839.62877671 574740.55366464
2376696.39940439574590.814134732
#Sta/Elev= 30
       0 2617.05   71.71 2566.02  142.97  2522.6  163.33 2514.52  199.19 2510.52
  312.05 2512.21  328.26 2512.05  426.26 2508.43  481.14 2509.56  589.12  2507.4
  614.45 2505.92  715.21 2504.16  733.42  2506.1  741.41  2500.4  773.36 2498.83
  785.33 2500.17  809.29 2500.56  849.22 2506.03  893.08  2501.9  913.02 2505.73
 1044.61  2506.7 1068.53 2504.41 1096.44 2505.74 1111.57 2508.81 1124.36  2515.5
 1148.28 2534.49 1156.25 2537.77 1263.85 2550.48 1340.84 2567.69 1359.48 2571.22
#Mann= 12 ,-1 , 0
       0      .1       0  142.97     .06       0  312.05     .05       0
  328.26     .06       0  481.14     .05       0  589.12     .06       0
  614.45     .05       0  715.21      .1       0  741.41    .045       0
  785.33      .1       0 1111.57      .1       0 1340.84      .1       0
Bank Sta=741.41,785.33
XS Rating Curve= 0 ,0
Exp/Cntr=0.5,0.3

Type RM Length L Ch R = 1 ,0       ,0,0,0
XS GIS Cut Line= 3
2376513.84377286575736.1618507062377340.31029576574926.666094378
2377618.04432034574607.566338882
#Sta/Elev= 30
       0 2628.48  119.68 2545.92  167.55  2518.8  194.52 2510.88  319.13 2511.38
  529.84 2508.98  552.26 2508.71   697.5  2506.3  722.04 2505.09  757.94 2499.91
  795.33 2502.46  865.15 2502.54  916.86 2501.47  961.39 2502.11  985.33 2497.38
   997.3  2494.9 1065.11 2493.11 1088.13 2496.35 1097.02 2501.69    1105 2503.51
 1152.87 2500.94 1196.22 2501.14 1332.46 2500.92 1388.33 2502.54  1418.5 2508.09
 1432.23 2515.11 1468.15 2541.08 1512.05 2561.41 1524.03 2564.73  1579.9  2594.3
#Mann= 12 ,-1 , 0
       0      .1       0  194.52     .06       0  529.84     .05       0
  552.26     .06       0   697.5      .1       0  795.33     .06       0
  865.15     .05       0  916.86    .055       0  985.33    .045       0
 1088.13    .055       0 1196.22     .06       0  1418.5      .1       0
#XS Ineff= 2 , 0
             967  2503.6    1106          2503.6
Permanent Ineff=
       F       F
Bank Sta=985.33,1088.13
XS Rating Curve= 0 ,0
Exp/Cntr(USF)=0,0
Exp/Cntr=0.5,0.3
LCMann Table=0

Chan Stop Cuts=-1
Use User Specified Reach Order=0
Composite Channel Slope=5